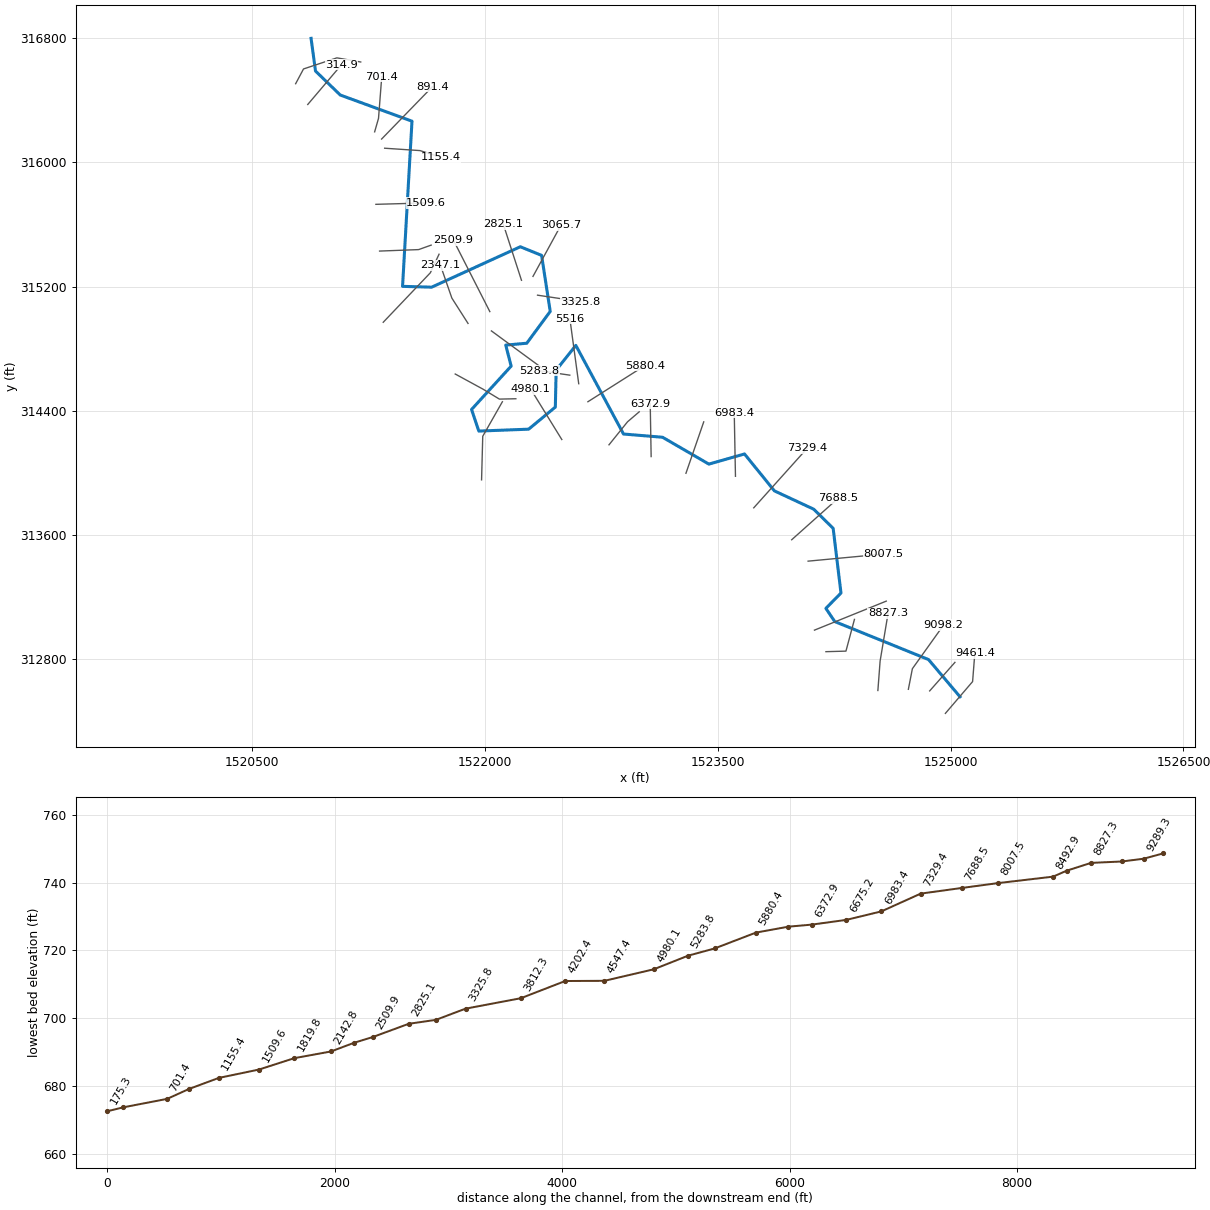
--- RockRn.prj (project) ---

Proj Title=RockRn
Current Plan=p01
Default Exp/Contr=0,0
English Units
Geom File=g01
Flow File=f01
Plan File=p01
BEGIN DESCRIPTION:
AMEC Environment & Infrastructure, 2013
Projection: NAD 1983 State Plane West Virginia North FIPS 4701 (US Feet)
Vertical Datum: NAVD 1988
END DESCRIPTION:
DSS Export Rating Curves= 0
DSS Export Rating Curve Sorted= 0
DSS Export Volume Flow Curves= 0
DXF OffsetX= 0
DXF OffsetY= 0
DXF ScaleX= 0
DXF ScaleY= 0

--- RockRn.p01 (plan) ---

Plan Title=Floodplain
Program Version=4.00
Geom File=g01
Flow File=f01
K Sum by GR=0
Std Step Tol=0.01
Critical Tol=0.01
Num of Std Step Trials=20
Max Error Tol=0.3
Flow Tol Ratio=0.001
Split Flow NTrial=30
Split Flow Tol=0.02
Split Flow Ratio=0.02
Log Output Level=0
Friction Slope Method=1
Unsteady Friction Slope Method=2
Unsteady Bridges Friction Slope Method=1
Global Log Level=0
CheckData=False
Run HTab=0
Run UNet=0
Run PostProcess=0
UNET Theta=0
UNET Theta Warmup=0
UNET ZTol=0
UNET ZSATol=0
UNET MxIter=0
UNET MaxInSteps=0
UNET DtIC=0
UNET DtMin=0
UNET MaxCRTS=0
UNET WFStab=0
UNET SFStab=0
UNET WFX=0
UNET SFX=0
UNET DSS MLevel=0
UNET DZMax Abort=0
UNET Convert EG Bridges=0
UNET Use Existing IB Tables=0
UNET Froude Limit=0
UNET Froude Power=0
Write IC File=0
Echo Input=False
Echo Output=False
Write Detailed=0

--- RockRn.f01 (steady flow) ---

Flow Title=USGS Regress. Eqn. (2010) - Western-Plateaus
Program Version=4.10
Number of Profiles= 1
Profile Names=P100yr
River Rch & RM=RockRn,Main            ,9461.4
    1290
River Rch & RM=RockRn,Main            ,8612.5
    1302
River Rch & RM=RockRn,Main            ,8007.5
    1421
River Rch & RM=RockRn,Main            ,4547.4
    1471
River Rch & RM=RockRn,Main            ,314.9
    1532
River Rch & RM=RockRn,Main            ,175.3
    1535
Boundary for River Rch & Prof#=RockRn,Main            , 1
Up Type= 0
Dn Type= 3
Dn Slope=0.00693
DSS Import GetInterval= 0
DSS Import GetPeak= 0
DSS Import FillOption= 0

--- RockRn.g01 (geometry) ---

Geom Title=USGS 3m DEM
Program Version=4.10

River Reach=RockRn          ,Main
Reach XY= 30
     1525060.331       312556.58     1524857.563      312796.371
     1524253.396      313041.162     1524196.105      313126.232
     1524293.327       313225.19      1524242.98      313641.857
      1524117.98      313765.121     1523864.508      313883.176
     1523671.778      314121.016     1523442.305      314055.719
     1523144.021      314228.662     1522892.285      314249.496
     1522584.994      314820.676     1522458.258      314660.954
     1522453.049      314423.107     1522281.174      314280.746
     1521959.994      314268.593     1521913.119      314407.482
     1522168.327      314686.996     1522133.605      314822.412
     1522269.021      314834.565     1522420.063      315039.426
     1522364.508      315400.537     1522227.355      315456.093
     1521656.174      315195.676     1521468.674      315200.885
     1521529.438      316265.121     1521067.633      316433.524
      1520907.91      316588.037     1520879.205      316798.878

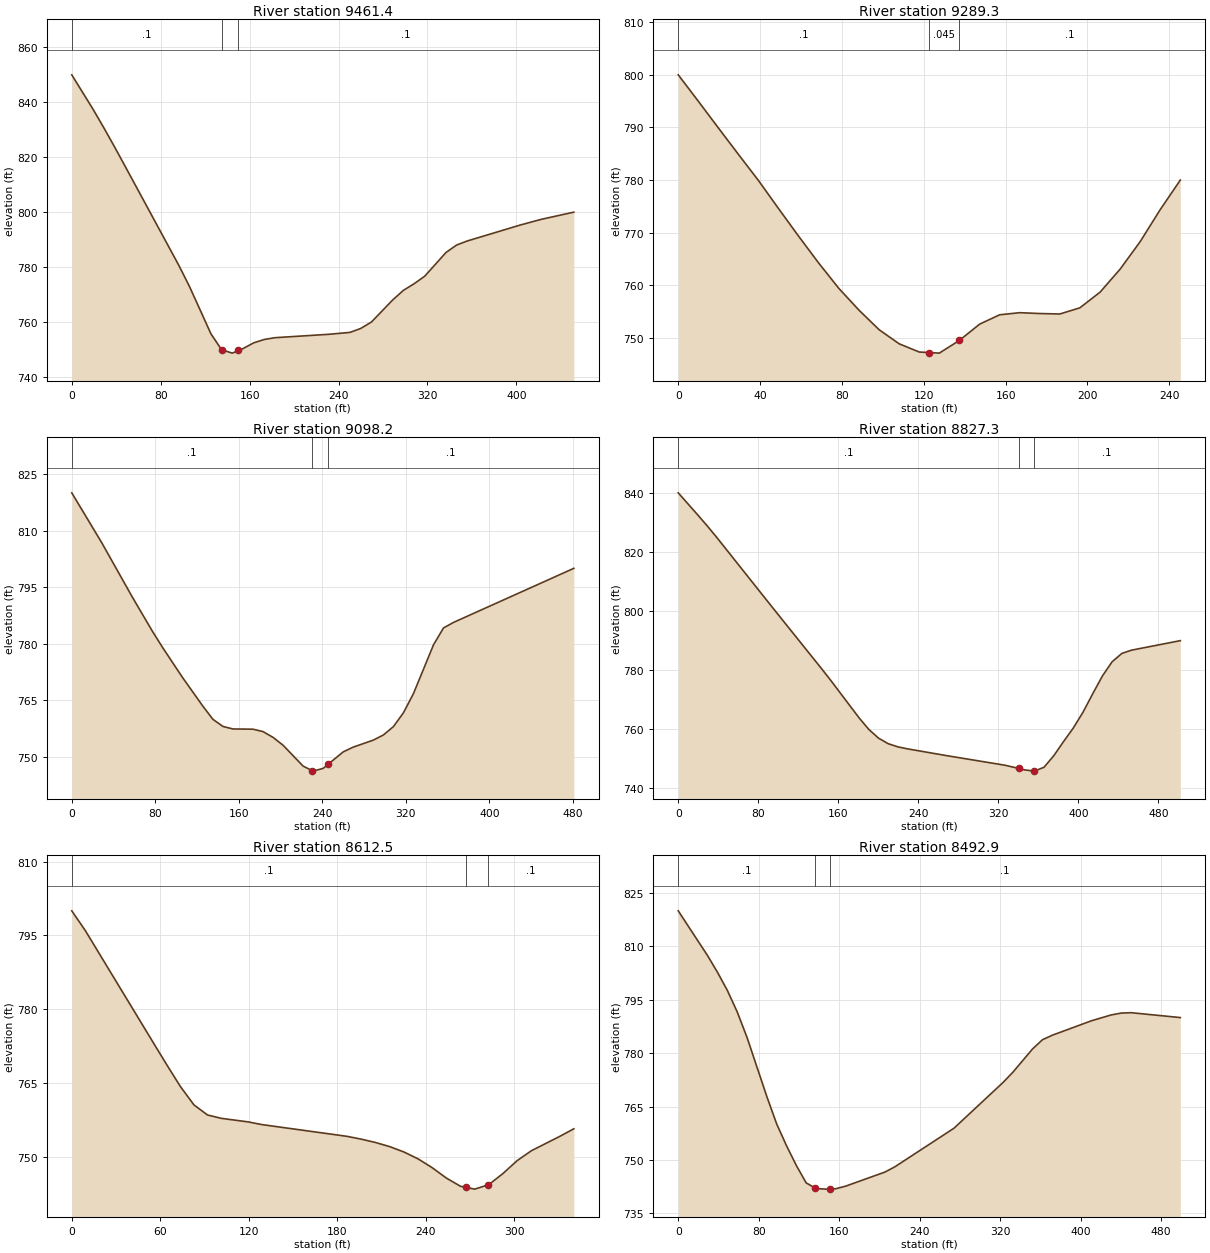
Type RM Length L Ch R = 1 ,9461.4  ,172.5,172.1,171.8
XS GIS Cut Line= 3
     1524966.096      312449.744     1525141.376      312654.552
     1525155.609      312836.108
#Sta/Elev= 30
       0     850    19.3  837.37    28.9  830.68    38.5  823.76    48.1  816.64
    96.3  780.64   105.9  772.94   125.2  755.71   134.8   749.9     135  749.87
   144.4  748.67     150  749.63     154  750.31   163.7  752.42   173.3  753.65
   182.9  754.29   231.1  755.52   250.3  756.22   259.9  757.63   269.6     760
   288.7  768.02   298.3  771.51   307.9  773.91   317.5  776.66   336.7  785.32
   346.2  788.02   355.8   789.5   403.8  795.35   422.9  797.43   451.7     800
#Mann= 3 , 0 , 0
       0      .1       0     135    .045       0     150      .1       0
Bank Sta=135,150
XS Rating Curve= 0 ,0
Exp/Cntr=0.3,0.1

Type RM Length L Ch R = 1 ,9289.3  ,188.8,191.1,193.4
XS GIS Cut Line= 2
     1524864.837      312594.548     1525027.464      312778.362
#Sta/Elev= 27
       0  800.01     9.8     795    19.6  789.92    29.4   784.9    39.3  779.87
    49.1  774.54    58.9  769.29    68.7   764.2    78.5   759.4    88.4  755.24
    98.2  751.54     108  748.86   117.8   747.3   122.4   747.2   127.6  747.09
   137.4   749.5   147.3   752.6   157.1  754.38   166.9  754.78   176.7  754.62
   186.5  754.53   196.3   755.7   206.2  758.69     216  763.07   225.8   768.3
   235.6  774.39   245.4     780
#Mann= 3 , 0 , 0
       0      .1       0   122.4    .045       0   137.4      .1       0
Bank Sta=122.4,137.4
XS Rating Curve= 0 ,0
Exp/Cntr=0.3,0.1

Type RM Length L Ch R = 1 ,9098.2  ,260.6,271,281.2
XS GIS Cut Line= 3
     1524727.565      312604.914     1524753.376      312737.617
      1524954.49      313018.846
#Sta/Elev= 30
       0     820      29  806.65    57.9  792.44    77.2  783.35    86.9  779.07
   106.2  771.04   125.5  763.52   135.2     760   144.8  758.12   154.4  757.45
   173.6  757.39   183.2  756.75   192.8  755.22   202.4  753.14   221.6  747.61
   230.5  746.38   231.2  746.28   240.8  747.01   245.5  748.08     260  751.38
   269.6  752.64   288.8  754.49   298.5  755.86   308.1  758.08   317.7  761.74
   327.3  766.83   346.5  779.75   356.1  784.22   365.7  785.68   480.9     800
#Mann= 3 , 0 , 0
       0      .1       0   230.5    .045       0   245.5      .1       0
Bank Sta=230.5,245.5
XS Rating Curve= 0 ,0
Exp/Cntr=0.3,0.1

Type RM Length L Ch R = 1 ,8827.3  ,217,214.8,212.6
XS GIS Cut Line= 3
     1524531.105      312597.091     1524545.528      312787.049
     1524596.818      313094.244
#Sta/Elev= 30
       0     840      19  832.73    28.6  828.97    38.1   825.1    95.2  800.81
   142.9   780.7   152.4  776.61     181  763.82   190.5     760   200.2  757.04
     210  755.14   219.7  754.07   229.4  753.39   268.4  751.11   326.8  747.86
   340.6  746.77   346.2   746.3   355.6  745.89     356  745.87   365.7  747.17
   375.4  751.04   385.2  755.84   394.9   760.4   404.6  765.72   414.4  772.02
   424.1  778.04   433.8  782.85   443.6  785.69   453.3  786.79     502     790
#Mann= 3 , 0 , 0
       0      .1       0   340.6    .045       0   355.6      .1       0
Bank Sta=340.6,355.6
XS Rating Curve= 0 ,0
Exp/Cntr=0.3,0.1

Type RM Length L Ch R = 1 ,8612.5  ,140.9,119.6,97.5
XS GIS Cut Line= 3
     1524196.464       312847.26     1524325.408      312850.753
     1524380.095       313055.18
#Sta/Elev= 28
       0     800     9.2  795.99    55.3  773.26    64.5  768.75    73.7  764.36
    82.9  760.63    92.1  758.59   101.4  757.91   119.8  757.18     129  756.64
   186.7  754.26   196.3  753.69   205.9  753.02   215.6  752.18   225.2   751.1
   234.8  749.71   244.4  747.92     254  745.82   263.7  744.13   267.2  743.92
   273.3  743.55   282.2  744.39   282.9  744.46   292.5  746.71   302.1  749.32
   311.8  751.34     331  754.24   340.6  755.79
#Mann= 3 , 0 , 0
       0      .1       0   267.2    .045       0   282.2      .1       0
Bank Sta=267.2,282.2
XS Rating Curve= 0 ,0
Exp/Cntr=0.3,0.1

Type RM Length L Ch R = 1 ,8492.9  ,492.2,485.4,506.7
XS GIS Cut Line= 2
     1524122.486      312986.025     1524585.163      313172.952
#Sta/Elev= 30
       0  819.99    29.4   807.3    39.1  802.68    48.9  797.59    58.7  791.54
    68.5  784.33    88.1  767.78    97.8  760.15   107.6  754.01   117.4  748.44
   127.2  743.54   135.7  742.18     137  741.97   146.8   741.8   150.7  741.84
   156.6  741.91   166.3  742.63   205.5   746.6   215.3  748.07     274   758.9
   322.9  771.79   332.7  774.68   352.2   781.2     362  783.77   371.8  785.04
     411  789.13   430.5  790.75   440.3  791.26   450.1  791.37     499     790
#Mann= 3 , 0 , 0
       0      .1       0   135.7    .045       0   150.7      .1       0
Bank Sta=135.7,150.7
XS Rating Curve= 0 ,0
Exp/Cntr=0.3,0.1

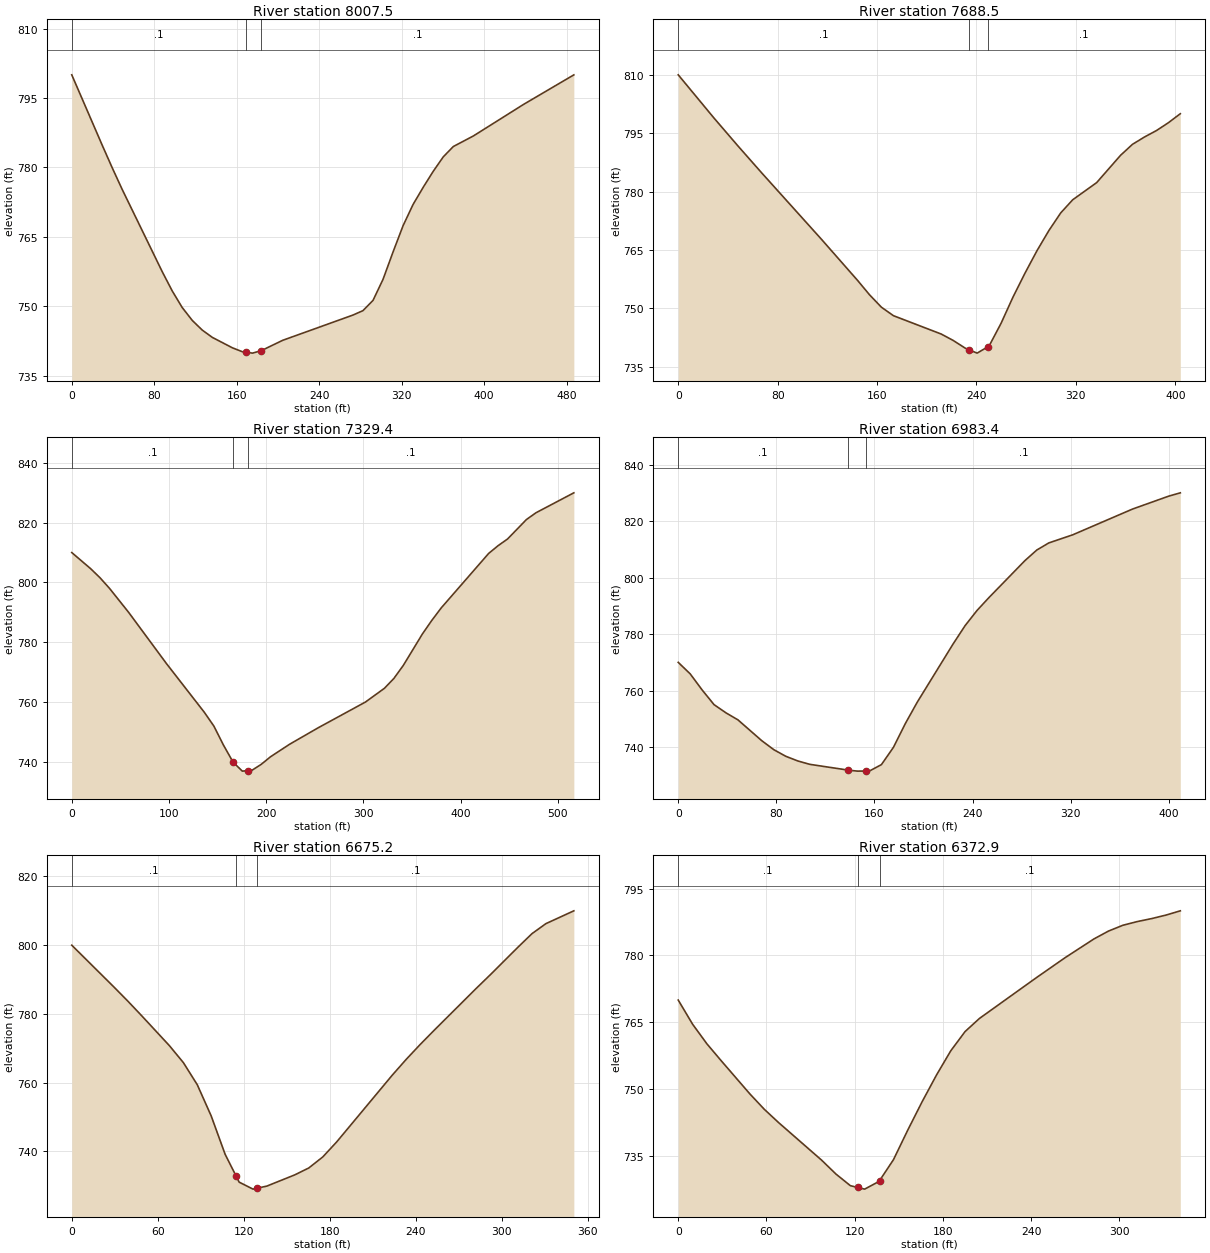
Type RM Length L Ch R = 1 ,8007.5  ,304.4,319,333.7
XS GIS Cut Line= 2
     1524081.538      313430.515     1524566.369      313476.125
#Sta/Elev= 30
       0  800.01    29.2  784.98      39  780.05    48.7  775.35    87.6  757.55
    97.4  753.34   107.1  749.75   116.9  746.95   126.6  744.86   136.4  743.28
   155.8  741.04   165.6  740.18   168.9  740.08   175.3  739.89   183.9  740.43
   204.5  742.65   272.7  748.11   282.4  749.06   292.2  751.28   301.9  755.82
   311.7  761.78   321.4  767.44   331.1  772.02   340.9  775.72   350.6  779.16
   360.4   782.3   370.1  784.52   389.6  786.81   438.3  793.63     487     800
#Mann= 3 , 0 , 0
       0      .1       0   168.9    .045       0   183.9      .1       0
Bank Sta=168.9,183.9
XS Rating Curve= 0 ,0
Exp/Cntr=0.3,0.1

Type RM Length L Ch R = 1 ,7688.5  ,356.6,359.1,361.5
XS GIS Cut Line= 2
     1523975.819      313568.329     1524277.095      313837.512
#Sta/Elev= 30
       0     810    28.9  798.84    48.1   791.7    67.3  784.74   115.4  767.66
   144.3  757.15   153.9  753.46   163.5  750.25   173.2  748.07   211.6  743.36
   221.2  741.72   230.9  739.74   234.1  739.31   240.5  738.45   249.1  740.07
   250.1  740.26   259.7  746.07   269.3  752.81     279     759   288.6  764.74
   298.2  769.94   307.8  774.51   317.4  777.87   336.7  782.29   355.9   789.3
   365.5  792.13   375.2  794.02   384.8  795.67   394.4  797.68     404     800
#Mann= 3 , 0 , 0
       0      .1       0   234.1    .045       0   249.1      .1       0
Bank Sta=234.1,249.1
XS Rating Curve= 0 ,0
Exp/Cntr=0.3,0.1

Type RM Length L Ch R = 1 ,7329.4  ,327.6,346,364.1
XS GIS Cut Line= 2
     1523731.338      313774.036     1524076.297      314158.365
#Sta/Elev= 30
       0     810    19.5  804.58    29.2  801.51      39  797.94    58.5  789.97
    97.4  772.81   136.4  756.47   146.2  751.86   155.9  745.59   165.9   739.8
   175.4  736.79   180.9  736.92   185.1  737.02   194.9  739.07   204.6  741.64
   224.1   745.8   253.4   751.3   302.1  759.94   321.6  764.54   331.3  767.83
     341   772.2   360.5  782.66   370.3  787.27     380  791.46   428.7  809.68
   438.5  812.31   448.2  814.54   467.7  821.08   477.5  823.34   516.4  830.01
#Mann= 3 , 0 , 0
       0      .1       0   165.9    .045       0   180.9      .1       0
Bank Sta=165.9,180.9
XS Rating Curve= 0 ,0
Exp/Cntr=0.3,0.1

Type RM Length L Ch R = 1 ,6983.4  ,316.4,308.2,299.9
XS GIS Cut Line= 2
     1523613.561      313977.233     1523605.697      314386.583
#Sta/Elev= 30
       0  770.02     9.8  765.92    19.5  760.25    29.2  755.06      39  752.14
    48.7  749.67    68.2  742.28      78  739.11    87.7  736.79    97.5  735.14
   107.2  733.95   138.5   731.9   146.2  731.54   153.5  731.58     156   731.6
   165.7  733.85   175.5  739.97   185.2  748.38     195  756.01   224.2  776.57
     234  783.06   243.7  788.41   253.4  792.95   282.7  806.01   292.4  809.76
   302.2  812.27   321.7  815.14   370.4  824.24   399.7  828.78   409.4  829.99
#Mann= 3 , 0 , 0
       0      .1       0   138.5    .045       0   153.5      .1       0
Bank Sta=138.5,153.5
XS Rating Curve= 0 ,0
Exp/Cntr=0.3,0.1

Type RM Length L Ch R = 1 ,6675.2  ,294.2,302.3,310.3
XS GIS Cut Line= 2
     1523294.548      313996.694     1523409.113      314327.794
#Sta/Elev= 28
       0     800    29.2  787.93    38.9  783.83    48.7  779.52    68.1  770.79
    77.9  765.83    87.6   759.4    97.3  750.33     107   739.2   114.6   732.9
   116.8  731.07   126.5  729.03   129.6  729.31   136.2  729.92   155.7  733.19
   165.4  735.18   175.2   738.4   184.9  742.77   223.8  762.25   233.6  766.87
   243.3  771.17     253  775.28   282.2   787.4     292  791.36   311.4  799.42
   321.2  803.36   330.9  806.27   350.4     810
#Mann= 3 , 0 , 0
       0      .1       0   114.6    .045       0   129.6      .1       0
Bank Sta=114.6,129.6
XS Rating Curve= 0 ,0
Exp/Cntr=0.3,0.1

Type RM Length L Ch R = 1 ,6372.9  ,224,208.2,192.4
XS GIS Cut Line= 2
     1523070.309      314104.207      1523064.35      314445.628
#Sta/Elev= 30
       0     770     9.8  764.58    19.5   760.2    29.3  756.38    48.8  748.95
    58.5  745.54    68.3  742.54    97.6  734.11   107.3  731.01   117.1  728.41
     122  728.02   126.8  727.64   136.6  729.37     137  729.57   146.4  734.24
   156.1  740.85   165.9  747.23   175.6  753.17   185.4  758.65   195.1  762.94
   204.9  765.89   243.9  775.09   263.4  779.56   282.9  783.73   292.7  785.47
   302.4  786.76   312.2  787.59     322  788.26   331.7  789.04   341.5     790
#Mann= 3 , 0 , 0
       0      .1       0     122    .045       0     137      .1       0
Bank Sta=122,137
XS Rating Curve= 0 ,0
Exp/Cntr=0.3,0.1

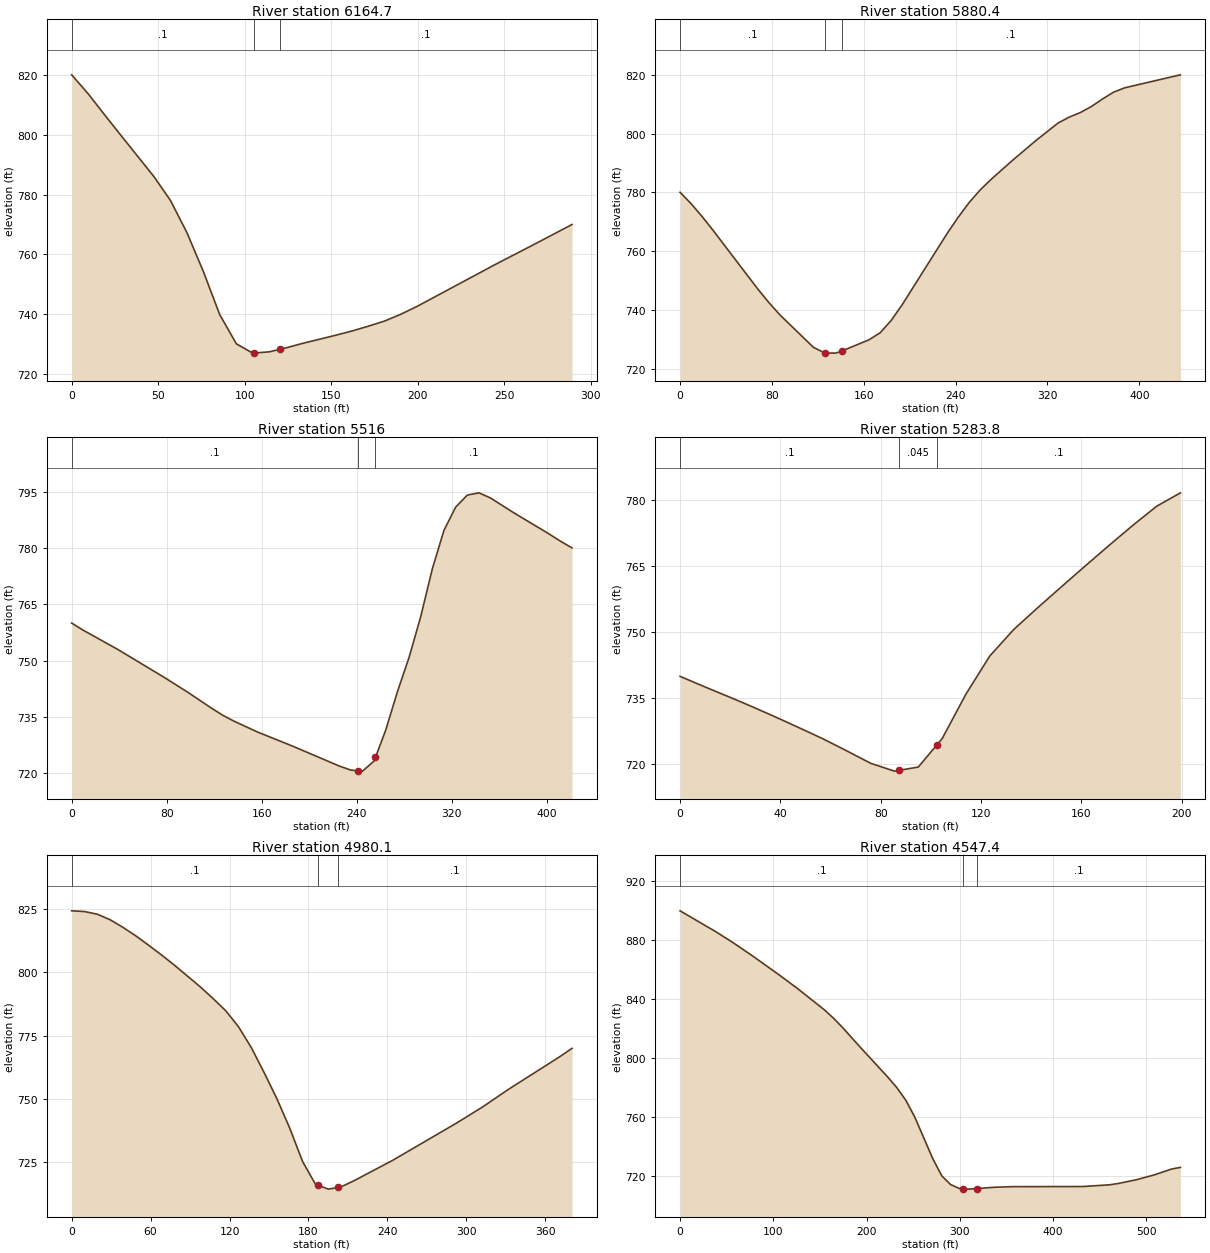
Type RM Length L Ch R = 1 ,6164.7  ,292.1,284.3,276.5
XS GIS Cut Line= 3
      1522798.72      314179.999     1522918.082      314328.223
     1522993.358      314392.532
#Sta/Elev= 25
       0  820.01     9.5   813.7      19  806.68    28.6  799.69    47.6  785.97
    57.1  778.05    66.6  767.32    76.1  754.35    85.6  739.89    95.2  730.14
   104.7  727.02   105.4  727.05   114.2  727.45   120.4  728.29   123.7  728.74
   133.2  730.23   152.2  732.93   161.8  734.37   171.3  735.98   180.8  737.71
   190.3     740   199.3  742.51   244.3  756.45   271.3  764.53   289.3     770
#Mann= 3 , 0 , 0
       0      .1       0   105.4    .045       0   120.4      .1       0
Bank Sta=105.4,120.4
XS Rating Curve= 0 ,0
Exp/Cntr=0.3,0.1

Type RM Length L Ch R = 1 ,5880.4  ,337.4,364.4,391.2
XS GIS Cut Line= 2
     1522662.913      314457.577     1523030.939      314690.924
#Sta/Elev= 30
       0  780.02     9.7  776.12    19.4  771.69      29  766.95    67.8  747.06
    77.5  742.43    87.2  738.21   116.2  727.25   126.1  725.32   135.6  725.28
   141.1  726.03   164.6  729.82   174.3  732.21     184  736.45   193.7  741.89
   232.4  765.86   242.1  771.44   251.8  776.53   261.5  780.86   271.1  784.49
   290.5   791.2   309.9  797.61   329.2  803.58   338.9  805.59   348.6  807.15
   358.3  809.22     368  811.79   377.7  814.12   387.4  815.59   435.8     820
#Mann= 3 , 0 , 0
       0      .1       0   126.1    .045       0   141.1      .1       0
Bank Sta=126.1,141.1
XS Rating Curve= 0 ,0
Exp/Cntr=0.3,0.1

Type RM Length L Ch R = 1 ,5516    ,203.1,232.2,261.1
XS GIS Cut Line= 2
     1522603.701      314573.707     1522546.875      314991.143
#Sta/Elev= 30
       0  759.98     9.8  758.07    39.2   752.9    78.4  745.44      98  741.52
   117.6  737.36   127.4  735.42   137.2  733.79   156.8  730.95   186.2  727.21
   225.3  721.94   235.1  720.85   240.8  720.69   244.9  720.58   254.7   723.3
   255.8  724.23   264.5  731.57   274.3  741.73   284.1  750.85   293.9   761.7
   303.7  774.44   313.5  784.68   323.3  790.83   333.1  794.04   342.9  794.65
   352.7  793.27   372.3  789.33   401.7  783.76   411.5  781.79   421.3  779.99
#Mann= 3 , 0 , 0
       0      .1       0   240.8    .045       0   255.8      .1       0
Bank Sta=240.8,255.8
XS Rating Curve= 0 ,0
Exp/Cntr=0.3,0.1

Type RM Length L Ch R = 1 ,5283.8  ,323.5,303.6,283.8
XS GIS Cut Line= 2
     1522546.223      314628.752     1522348.824      314657.785
#Sta/Elev= 24
       0     740     9.5   737.7      19  735.46    28.5  733.17      38  730.78
    47.5  728.31      57   725.8    66.5  723.06      76  720.24    85.5  718.46
    87.3  718.64      95  719.39   102.3  724.35   104.5  725.84     114  735.97
   123.5  744.62     133  750.62   142.5  755.54     152  760.33   161.5  765.06
     171  769.73   180.5   774.3     190  778.65   199.5  781.71
#Mann= 3 , 0 , 0
       0      .1       0    87.3    .045       0   102.3      .1       0
Bank Sta=87.3,102.3
XS Rating Curve= 0 ,0
Exp/Cntr=0.3,0.1

Type RM Length L Ch R = 1 ,4980.1  ,457.3,432.7,408.1
XS GIS Cut Line= 2
     1522494.679      314214.035     1522295.041      314537.879
#Sta/Elev= 30
       0   824.3     9.8  824.02    19.5  822.96    29.3  820.76      39  817.77
    48.8   814.4    58.5  810.72    68.3  806.88      78  802.89    97.6  794.36
   107.3  789.77   117.1  784.87   126.8  778.56   136.6  770.27   146.3  760.46
   156.1  750.03   165.8  738.49   175.6  725.28   185.3  716.37   187.4  715.95
   195.1  714.42   202.4  715.08   204.8   715.3   214.6  717.72   243.9  725.75
   292.6   740.5   312.2  746.79   331.7  753.69   370.7  766.58   380.4     770
#Mann= 3 , 0 , 0
       0      .1       0   187.4    .045       0   202.4      .1       0
Bank Sta=187.4,202.4
XS Rating Curve= 0 ,0
Exp/Cntr=0.3,0.1

Type RM Length L Ch R = 1 ,4547.4  ,382,345,308.1
XS GIS Cut Line= 3
     1521977.791       313954.37     1521985.322      314235.052
     1522111.866      314457.524
#Sta/Elev= 30
       0     900    38.7   885.7    58.1  877.87    77.5   869.5   106.5  856.42
   125.9  847.29   154.9  832.74   164.6   827.1   174.3  820.78   193.6  807.18
   222.7  787.19   232.4  780.05     242  771.56   251.7  760.06   271.1   731.7
   280.8     720   290.3   714.1   299.7  711.45     303   711.3   309.2  711.03
     318   711.4   337.7  712.32   356.6  712.71   432.4   712.8   460.9  713.98
   470.4  714.89   489.3  717.38   508.3  720.62   527.2  724.66   536.7   725.8
#Mann= 3 , 0 , 0
       0      .1       0     303    .045       0     318      .1       0
Bank Sta=303,318
XS Rating Curve= 0 ,0
Exp/Cntr=0.3,0.1

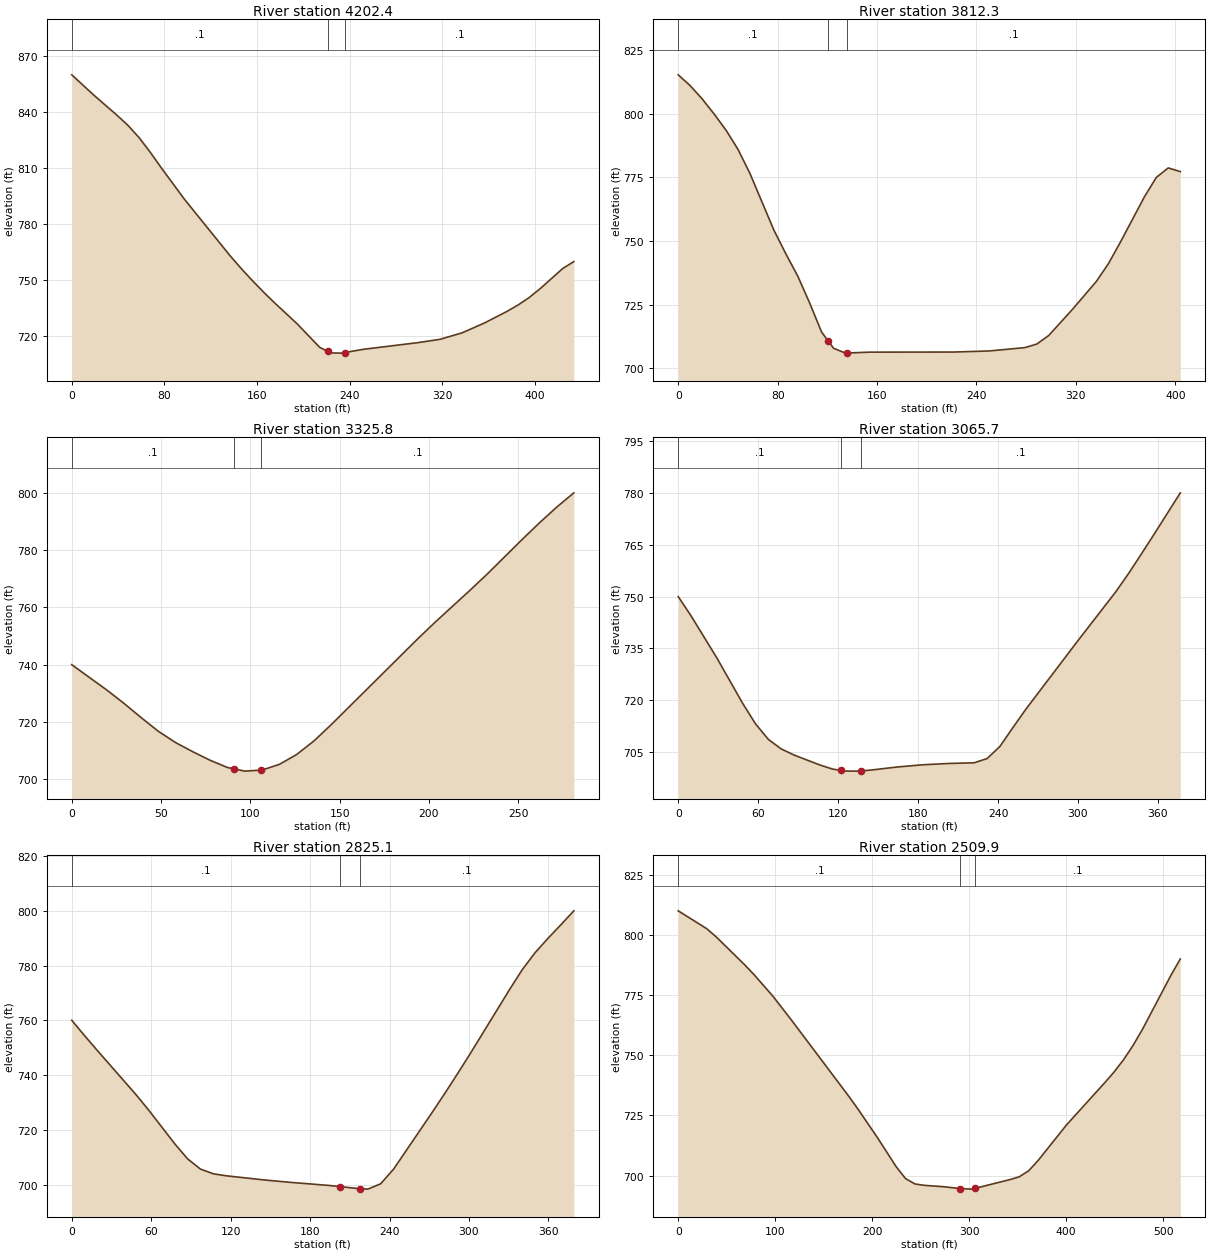
Type RM Length L Ch R = 1 ,4202.4  ,392.3,390.1,389.1
XS GIS Cut Line= 4
     1521808.048      314636.174     1521987.634      314538.226
     1522092.665      314474.508     1522198.609      314476.832
#Sta/Elev= 30
       0     860    19.5  848.87      39  838.39    48.7  832.83    58.4  826.15
    68.2  818.16    77.9  809.67    97.4  793.26   136.4  763.33   146.1  756.39
   155.9  749.81   165.6  743.61   175.3  737.77   194.8  726.52     214  714.08
   220.8  711.93   223.5  711.08   232.9  710.97   235.8  711.29   251.8  713.02
   299.1  716.61     318  718.38     337  721.84   356.3  727.13   375.6  733.28
   385.2  736.72   394.8  740.72   404.5  745.58   423.7  756.23   433.4  760.02
#Mann= 3 , 0 , 0
       0      .1       0   220.8    .045       0   235.8      .1       0
Bank Sta=220.8,235.8
XS Rating Curve= 0 ,0
Exp/Cntr=0.3,0.1

Type RM Length L Ch R = 1 ,3812.3  ,475.6,486.6,496.3
XS GIS Cut Line= 2
     1522041.203       314913.86     1522366.997      314675.021
#Sta/Elev= 30
       0  815.37     9.6  811.11    19.2  805.94    28.8  800.01    38.5  793.58
    48.1  786.04    57.7  776.58      77  754.24    86.6  744.96    96.2  736.17
   105.8  725.55   115.4  714.14   120.4  710.84     125  707.81   134.6  705.89
   135.4  705.91   153.9  706.28   221.2  706.31   250.1  706.74   278.9  708.05
   288.5  709.45   298.2  712.86   317.4  723.21   336.6  734.19   346.2  741.12
   355.9  749.64   375.1  767.37   384.7  775.01   394.3  778.75     404   777.3
#Mann= 3 , 0 , 0
       0      .1       0   120.4    .045       0   135.4      .1       0
Bank Sta=120.4,135.4
XS Rating Curve= 0 ,0
Exp/Cntr=0.3,0.1

Type RM Length L Ch R = 1 ,3325.8  ,229.3,260.1,291.9
XS GIS Cut Line= 2
     1522338.389      315144.137     1522616.336       315102.41
#Sta/Elev= 25
       0  739.99    19.4  731.23    29.1  726.54    38.8  721.52    48.5   716.7
    58.2  712.75    67.8  709.56    77.5  706.58    87.2  704.06    90.9  703.58
    96.9   702.8   105.9  703.15   106.6  703.18   116.3  705.18     126  708.64
   135.7   713.4   145.4  719.12   193.8  749.08   203.5  754.86   222.9  765.94
   232.6  771.64     252  783.62   261.7  789.45   271.4  794.96   281.1  800.02
#Mann= 3 , 0 , 0
       0      .1       0    90.9    .045       0   105.9      .1       0
Bank Sta=90.9,105.9
XS Rating Curve= 0 ,0
Exp/Cntr=0.3,0.1

Type RM Length L Ch R = 1 ,3065.7  ,224.9,240.6,255
XS GIS Cut Line= 2
     1522309.045      315265.124     1522489.601      315595.852
#Sta/Elev= 29
       0  749.98     9.7  744.37      29  732.24    48.3  719.14      58  713.18
    67.6  708.69    77.3  705.92      87  704.14   106.3  701.28   115.9  700.09
   122.5   699.7   125.6  699.52   135.3   699.5   137.5  699.57   144.9  699.82
   164.2  700.69   183.6  701.34   202.9  701.71   222.2  701.92   231.9  703.15
   241.5  706.68   251.2  712.12   260.9  717.41   299.5     737   328.5  751.44
   338.2  756.79   347.8  762.44   357.5  768.24   376.8     780
#Mann= 3 , 0 , 0
       0      .1       0   122.5    .045       0   137.5      .1       0
Bank Sta=122.5,137.5
XS Rating Curve= 0 ,0
Exp/Cntr=0.3,0.1

Type RM Length L Ch R = 1 ,2825.1  ,311.4,315.2,318.9
XS GIS Cut Line= 2
     1522234.867      315240.158     1522117.898      315600.848
#Sta/Elev= 29
       0  760.01     9.7  754.38    19.4  748.92    48.6   732.8    58.3  727.06
    77.8  714.87    87.5  709.37    97.2  705.64     107  703.91   116.7  703.19
   145.8  701.65   165.3  700.79   194.4  699.66   202.5  699.26   213.9  698.64
   217.5  698.52   223.6  698.32   233.3  700.27   243.1  705.65   272.2  726.35
     282  733.48   291.7  740.73   301.4  748.18   330.6   771.2   340.3  778.54
     350  784.74   359.7  789.96   369.5  794.95   379.2     800
#Mann= 3 , 0 , 0
       0      .1       0   202.5    .045       0   217.5      .1       0
Bank Sta=202.5,217.5
XS Rating Curve= 0 ,0
Exp/Cntr=0.3,0.1

Type RM Length L Ch R = 1 ,2509.9  ,166,162.9,159.9
XS GIS Cut Line= 2
     1522030.993      315038.147     1521796.015      315499.503
#Sta/Elev= 30
       0  809.99    29.3  802.59    39.1  799.19    68.4  787.63    78.2  783.48
    97.7  774.52   117.2  764.39   175.8  733.03   185.6  727.53   205.2  715.96
   224.7  703.78   234.4  698.81   244.2  696.56     254  695.98   273.5  695.43
   290.9  694.65   302.8  694.42   305.9  694.72   341.9  698.36   351.7  699.53
   361.4  702.03   371.2  706.34   400.5  721.11   439.6  738.49   449.4  743.01
   459.1  748.06   468.9  753.98   478.7  760.72     508  783.12   517.8     790
#Mann= 3 , 0 , 0
       0      .1       0   290.9    .045       0   305.9      .1       0
Bank Sta=290.9,305.9
XS Rating Curve= 0 ,0
Exp/Cntr=0.3,0.1

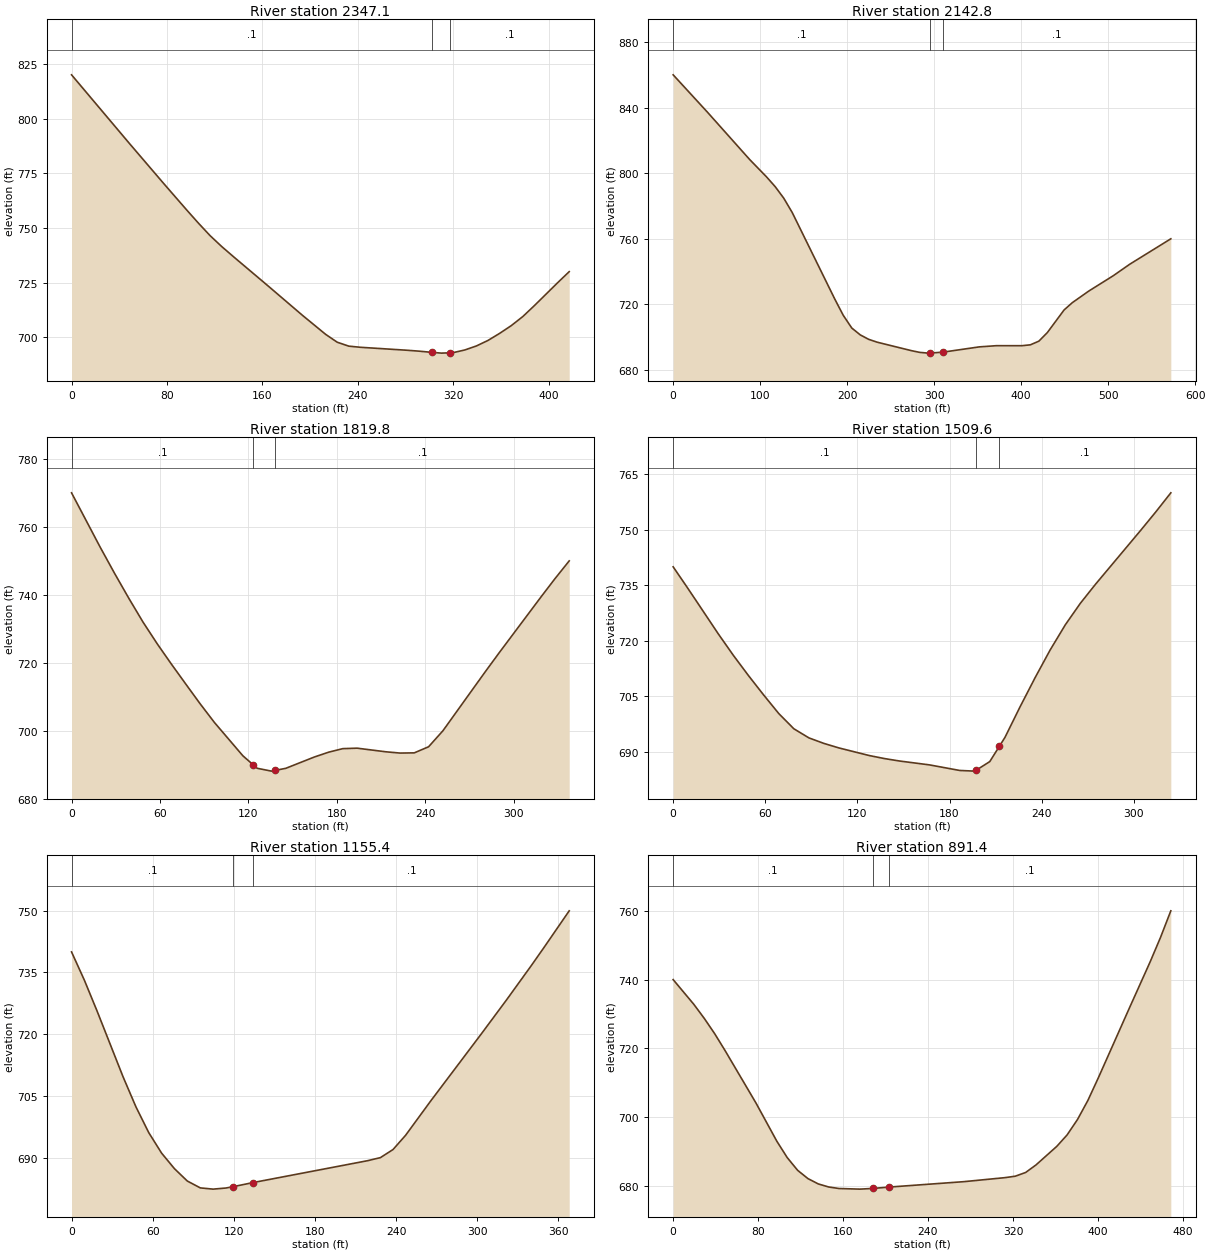
Type RM Length L Ch R = 1 ,2347.1  ,231.4,204.2,175.2
XS GIS Cut Line= 3
     1521890.489      314962.116     1521786.372      315125.288
      1521713.01      315336.446
#Sta/Elev= 29
       0  820.01    48.4  788.69    77.4   770.2    96.8  758.03   106.5  752.09
   116.1  746.48   125.8  741.51   135.5  736.94   164.5  723.57   193.6     710
     213  701.31   222.7  697.72   232.4  695.93   242.2  695.41     281  694.06
   290.8  693.66     302  693.09   310.2  692.74     317   692.9   319.9  692.97
   329.6  694.18   339.4  696.04   349.1  698.56   358.8  701.78   368.5   705.3
   378.2  709.46   387.9  714.46   407.4  724.94   417.1     730
#Mann= 3 , 0 , 0
       0      .1       0     302    .045       0     317      .1       0
Bank Sta=302,317
XS Rating Curve= 0 ,0
Exp/Cntr=0.3,0.1

Type RM Length L Ch R = 1 ,2142.8  ,338.6,323,309
XS GIS Cut Line= 3
     1521344.252       314969.62     1521647.641        315288.2
     1521703.753      315407.862
#Sta/Elev= 30
       0  860.02    39.1   837.4      88   808.3   107.5  797.64   117.3  791.76
   127.1  784.75   136.9  775.95   185.8  723.15   195.5  713.27   205.3  705.49
   215.1  701.29   224.8  698.57   234.6  696.82   273.7  691.69   283.5  690.61
   293.3  690.16   295.1  690.18   310.1  690.75   351.9  693.97   371.5   694.7
   400.8  694.69   410.6  695.22   420.4  697.46   430.2  702.74   449.4  716.51
   458.8  720.94   477.7  728.01     506  737.43   524.9  744.43   572.1  759.94
#Mann= 3 , 0 , 0
       0      .1       0   295.1    .045       0   310.1      .1       0
Bank Sta=295.1,310.1
XS Rating Curve= 0 ,0
Exp/Cntr=0.3,0.1

Type RM Length L Ch R = 1 ,1819.8  ,310.4,310.1,309.8
XS GIS Cut Line= 3
     1521320.628      315428.279     1521572.309      315437.777
     1521652.989      315466.692
#Sta/Elev= 30
       0  770.01    19.4  754.05    29.1   746.4    38.8  739.04    48.4  732.06
    58.1  725.63    67.8  719.61    77.5  713.78    87.2     708    96.9   702.5
   116.2   692.7   123.3  690.01   125.9  689.02   135.6  688.18   138.3  688.41
   145.3     689   164.7  692.33   174.4  693.75     184  694.79   193.7  694.93
   213.1  693.87   222.8  693.49   232.5  693.55   242.2  695.34   251.9  700.03
   280.4  717.25     290  722.93   318.5  739.42     328   744.8   337.6     750
#Mann= 3 , 0 , 0
       0      .1       0   123.3    .045       0   138.3      .1       0
Bank Sta=123.3,138.3
XS Rating Curve= 0 ,0
Exp/Cntr=0.3,0.1

Type RM Length L Ch R = 1 ,1509.6  ,356.3,354.3,352.2
XS GIS Cut Line= 2
     1521296.982      315729.435     1521620.958      315738.451
#Sta/Elev= 30
       0  740.01     9.8  734.06    29.5  721.83    39.3  716.04    49.1   710.6
    58.9  705.41    68.8  700.36    78.6  696.26    88.4   693.8    98.2   692.3
     108  691.08   127.7  689.03   137.5  688.22   147.3  687.56     167   686.5
   186.6     685   196.4  684.82   197.4  685.08   206.2   687.4   212.4   691.5
   216.1  693.95   225.9  702.18   235.7  710.06   245.5  717.54   255.4  724.36
   265.2  730.17     275  735.28   304.5  749.88   314.3  754.84   324.1     760
#Mann= 3 , 0 , 0
       0      .1       0   197.4    .045       0   212.4      .1       0
Bank Sta=197.4,212.4
XS Rating Curve= 0 ,0
Exp/Cntr=0.3,0.1

Type RM Length L Ch R = 1 ,1155.4  ,244.6,263.9,281.7
XS GIS Cut Line= 3
     1521353.375      316090.946     1521581.257        316075.6
     1521714.487      316033.786
#Sta/Elev= 24
       0     740     9.5  733.12      19  725.53    38.1  709.64    47.6  702.35
    57.1  696.07    66.6  691.09    76.1  687.31    85.6  684.31    95.2  682.64
   104.7  682.34   114.2  682.61   119.5  682.94   134.5  683.95   218.9  689.25
   228.4     690   237.7  691.96     247  695.42   265.6  703.78   302.9  720.03
   321.5  728.27   340.1  736.74   349.4   741.1     368  749.99
#Mann= 3 , 0 , 0
       0      .1       0   119.5    .045       0   134.5      .1       0
Bank Sta=119.5,134.5
XS Rating Curve= 0 ,0
Exp/Cntr=0.3,0.1

Type RM Length L Ch R = 1 ,891.4   ,171.2,190.1,209.1
XS GIS Cut Line= 2
     1521333.698      316150.009     1521660.151      316486.305
#Sta/Elev= 30
       0  739.99    19.5  732.79    29.3  728.71    39.1  724.26    48.8   719.4
    78.1  704.04    97.6  693.01   107.4  688.23   117.2  684.53   126.9  682.12
   136.7  680.56   146.5  679.67   156.2  679.23   175.8  679.05   188.1  679.25
   203.1  679.64   273.4  681.21   312.5  682.39   322.2  682.81     332   683.9
   341.8  686.11   361.3  691.49     371  694.81   380.8   699.3   390.6  704.86
   400.3  711.34   429.6  731.68   449.2  745.14   458.9   752.2   468.7     760
#Mann= 3 , 0 , 0
       0      .1       0   188.1    .045       0   203.1      .1       0
Bank Sta=188.1,203.1
XS Rating Curve= 0 ,0
Exp/Cntr=0.3,0.1

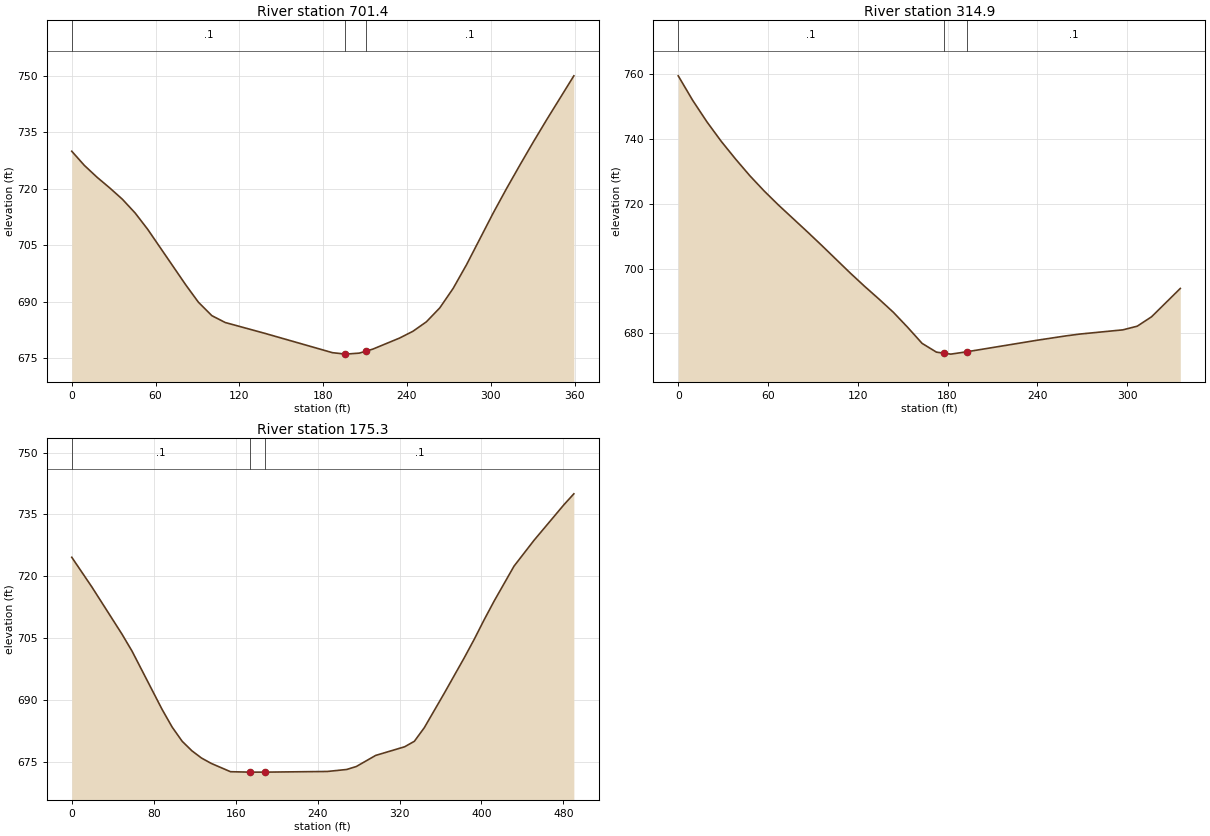
Type RM Length L Ch R = 1 ,701.4   ,402.1,386.5,372.2
XS GIS Cut Line= 3
     1521288.816      316196.317     1521313.875      316283.524
     1521334.614      316551.454
#Sta/Elev= 30
       0     730     9.1  726.21    18.2  723.07    27.2  720.26    36.3  717.24
    45.4   713.6    54.4  709.26    81.7  694.49    90.7  689.92   100.3  686.36
   109.9  684.54   138.7  681.62   186.7  676.53   195.7  676.17   196.3  676.15
   205.9  676.42   210.7  676.94   215.5  677.47   234.7  680.41   244.3  682.22
   253.9  684.72   263.5  688.42   273.1  693.61   282.7  699.91   301.9   713.7
   311.5  720.22   321.1  726.48   330.7   732.6   340.3  738.52   359.5  750.02
#Mann= 3 , 0 , 0
       0      .1       0   195.7    .045       0   210.7      .1       0
Bank Sta=195.7,210.7
XS Rating Curve= 0 ,0
Exp/Cntr=0.3,0.1

Type RM Length L Ch R = 1 ,314.9   ,152.1,139.6,127
XS GIS Cut Line= 2
     1520857.997      316372.775      1521075.12       316628.68
#Sta/Elev= 27
       0  759.32     9.6  751.82    19.2  745.14    28.8  739.12    38.4  733.66
    47.9  728.55    57.5  723.84    67.1   719.5    86.3  711.31    95.9  707.12
   115.1  698.56   124.6  694.51   134.2  690.59   143.8  686.53   153.4  681.88
     163  676.96   172.6  674.26   177.7  673.94   182.2  673.65   192.7  674.36
   239.7  677.91   258.9  679.25   268.5  679.83   297.2  681.12   306.8  682.25
   316.4  685.15   335.6  693.87
#Mann= 3 , 0 , 0
       0      .1       0   177.7    .045       0   192.7      .1       0
Bank Sta=177.7,192.7
XS Rating Curve= 0 ,0
Exp/Cntr=0.3,0.1

Type RM Length L Ch R = 1 ,175.3   ,179.9,175.3,170.8
XS GIS Cut Line= 4
     1520779.929      316506.454     1520830.605      316601.638
     1521045.702      316673.043     1521199.176      316646.465
#Sta/Elev= 30
       0  724.61    19.6  717.42      49  705.98    58.8  701.87    88.2  687.71
      98  683.43   107.8  679.98   117.3  677.67   126.7  675.91   136.2  674.61
     155   672.6   173.9   672.5     174   672.5     189   672.5   249.5  672.66
   268.4  673.14   277.8  673.86   296.7  676.55     325  678.65   334.5  679.98
   344.2  683.28   363.7  691.64   383.2  700.23   392.9   704.7   402.6  709.44
   412.4     714   431.8  722.46   451.3  728.72   480.5  737.35   490.2     740
#Mann= 3 , 0 , 0
       0      .1       0     174    .045       0     189      .1       0
Bank Sta=174,189
XS Rating Curve= 0 ,0
Exp/Cntr=0.3,0.1

Chan Stop Cuts=-1
Use User Specified Reach Order=0
Composite Channel Slope=5